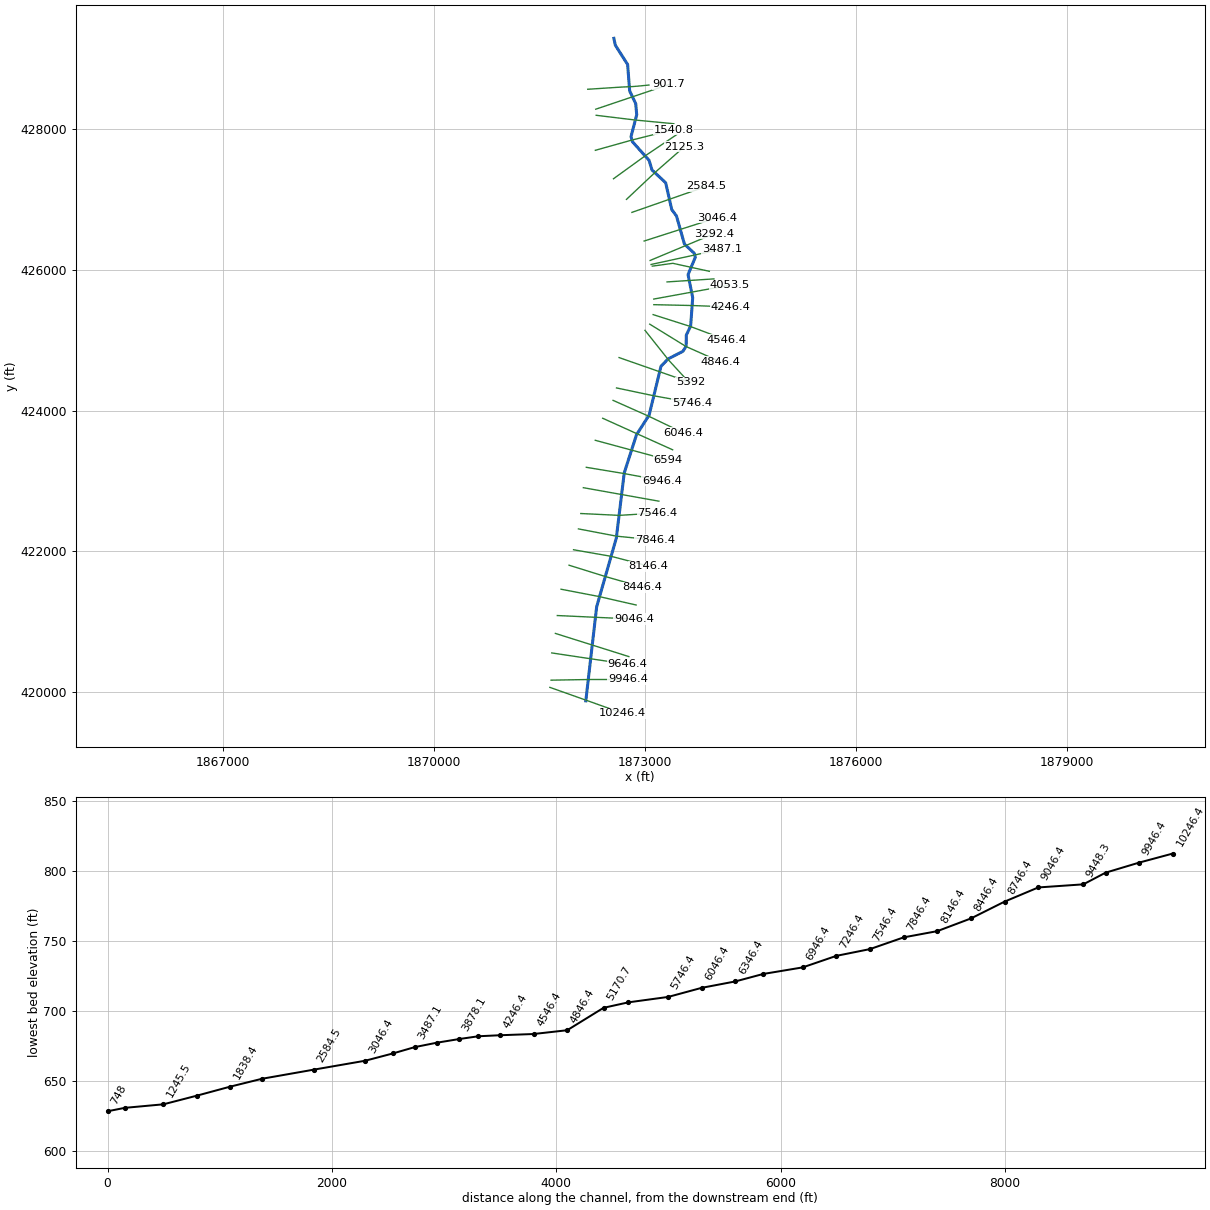
--- MorrisCrk.prj (project) ---

Proj Title=MorrisCrk
Current Plan=p01
Default Exp/Contr=0,0
English Units
Geom File=g01
Flow File=f01
Plan File=p01
BEGIN DESCRIPTION:
END DESCRIPTION:
DSS Export Rating Curves= 0
DSS Export Rating Curve Sorted= 0
DSS Export Volume Flow Curves= 0
DXF OffsetX= 0
DXF OffsetY= 0
DXF ScaleX= 0
DXF ScaleY= 0

--- MorrisCrk.p01 (plan) ---

Plan Title=Floodplain
Program Version=4.00
Geom File=g01
Flow File=f01
K Sum by GR=0
Std Step Tol=0.01
Critical Tol=0.01
Num of Std Step Trials=20
Max Error Tol=0.3
Flow Tol Ratio=0.001
Split Flow NTrial=30
Split Flow Tol=0.02
Split Flow Ratio=0.02
Log Output Level=0
Friction Slope Method=1
Unsteady Friction Slope Method=2
Unsteady Bridges Friction Slope Method=1
Global Log Level=0
CheckData=False
Run HTab=0
Run UNet=0
Run PostProcess=0
UNET Theta=0
UNET Theta Warmup=0
UNET ZTol=0
UNET ZSATol=0
UNET MxIter=0
UNET MaxInSteps=0
UNET DtIC=0
UNET DtMin=0
UNET MaxCRTS=0
UNET WFStab=0
UNET SFStab=0
UNET WFX=0
UNET SFX=0
UNET DSS MLevel=0
UNET DZMax Abort=0
UNET Convert EG Bridges=0
UNET Use Existing IB Tables=0
UNET Froude Limit=0
UNET Froude Power=0
Write IC File=0
Echo Input=False
Echo Output=False
Write Detailed=0

--- MorrisCrk.f01 (steady flow) ---

Flow Title=NFF Regression Equation
Program Version=4.10
Number of Profiles= 1
Profile Names=P100yr
River Rch & RM=MorrisCrk,Main            ,10246.4
1340.407
River Rch & RM=MorrisCrk,Main            ,6946.4
1479.372
River Rch & RM=MorrisCrk,Main            ,6594
1913.417
River Rch & RM=MorrisCrk,Main            ,4846.4
1954.539
Boundary for River Rch & Prof#=MorrisCrk,Main            , 1
Up Type= 0
Dn Type= 1
Dn Known WS=637
DSS Import GetInterval= 0
DSS Import GetPeak= 0
DSS Import FillOption= 0

--- MorrisCrk.g01 (geometry) ---

Geom Title=USGS 3m DEM
Program Version=4.10

River Reach=MorrisCrk       ,Main
Reach XY= 30
      1872158.64      419873.146     1872313.154      421211.687
     1872592.667      422189.118     1872705.515      423116.201
     1872879.126      423656.132     1873059.822      423938.407
     1873228.084      424631.826     1873328.779      424735.993
     1873540.584      424845.368     1873586.524      424916.549
     1873588.347       425076.21     1873649.959      425203.007
     1873679.473      425607.521     1873613.314      425935.473
     1873716.602      426182.099     1873702.109      426238.545
     1873561.758      426369.743     1873448.339      426769.942
      1873381.59       426860.25     1873294.707      427242.208
     1873100.486      427423.612     1873058.093      427561.637
     1872822.372      427825.548     1872801.853      427898.751
     1872882.713      428209.484     1872868.905      428365.977
     1872782.604      428547.786     1872753.449      428924.483
      1872578.63      429197.637     1872557.812      429296.429

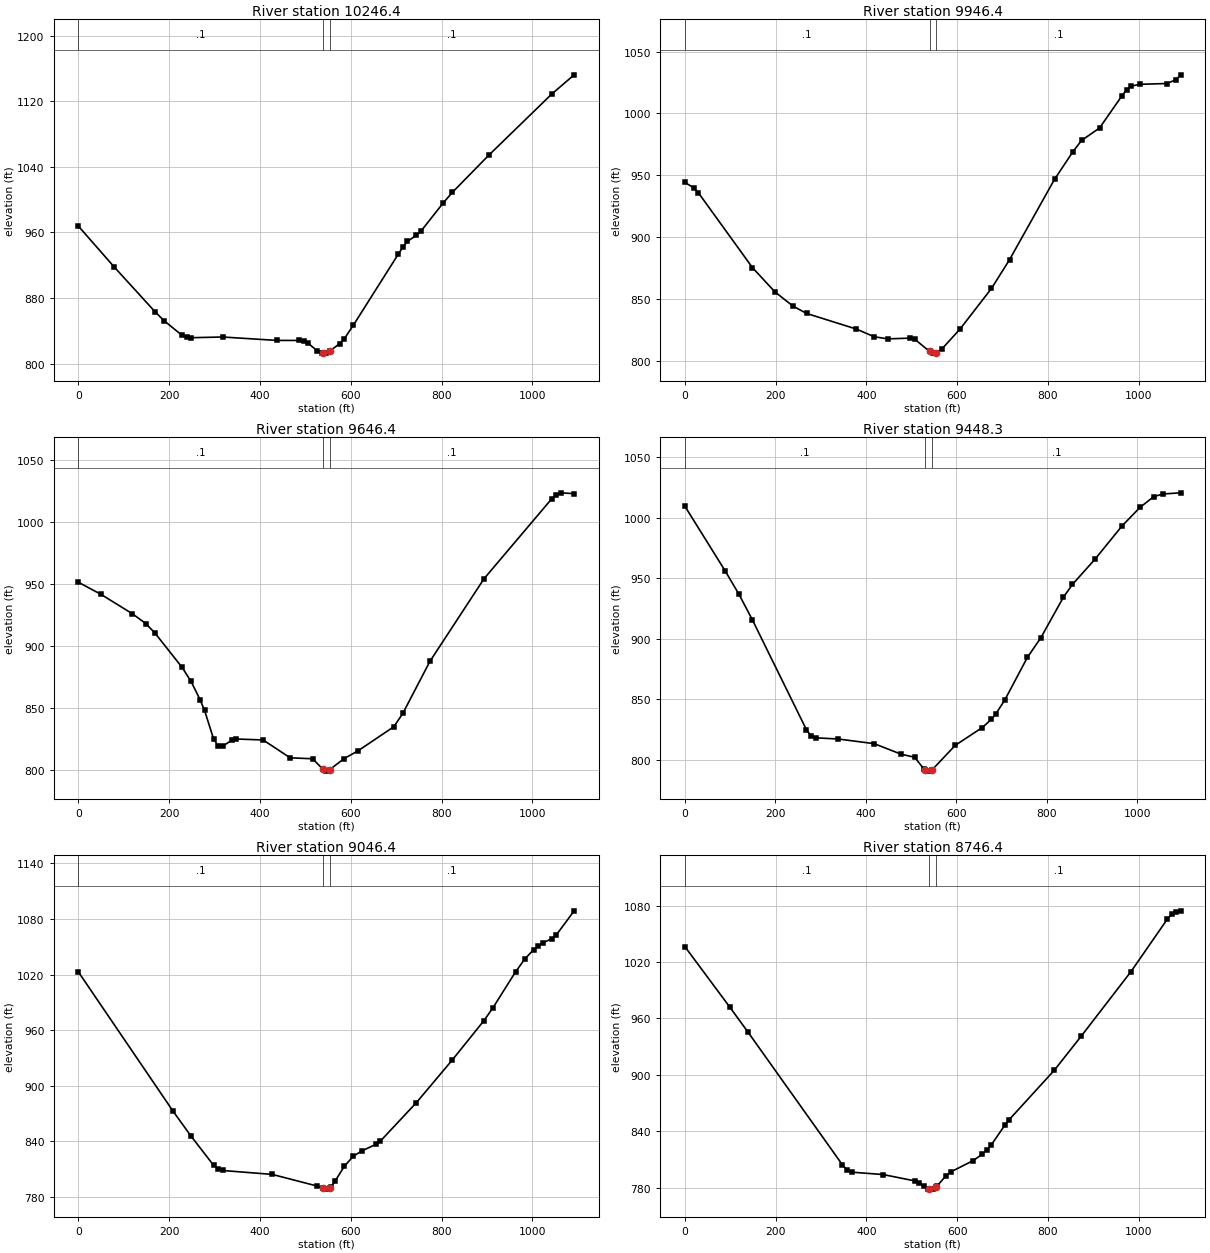
Type RM Length L Ch R = 1 ,10246.4 ,291.9,299.9,307.7
XS GIS Cut Line= 3
     1871647.303      420064.778     1872162.003      419882.563
     1872676.194      419698.924
#Sta/Elev= 30
       0  967.82    79.4  917.65   168.8   863.3   188.6   852.4   228.3  834.51
   238.3  832.08   248.2  831.54   317.7   832.4   436.8  828.24   486.4  828.19
   496.4  827.41   506.3  824.68   526.2   815.5   536.1  812.72   538.5  812.77
     546  812.94   553.5  815.11   575.8   824.4   585.7   830.2   605.6   846.7
   704.8  933.63   714.8  942.17   724.7  949.12   744.6  956.51   754.5  961.54
   804.1  996.38     824 1009.08   903.4    1054  1042.4 1128.84    1092 1152.44
#Mann= 3 , 0 , 0
       0      .1       0   538.5    .045       0   553.5      .1       0
Bank Sta=538.5,553.5
XS Rating Curve= 0 ,0
Exp/Cntr=0.3,0.1

Type RM Length L Ch R = 1 ,9946.4  ,303.7,300,296.6
XS GIS Cut Line= 3
     1871663.967      420167.301     1872210.723      420176.752
     1872756.575      420176.752
#Sta/Elev= 30
       0  944.27    19.9  939.82    29.8  935.91   149.1  875.35   198.8  855.66
   238.6  844.23   268.4  838.32   377.8  825.72   417.6  819.46   447.4  817.76
   497.1  818.37   507.1  817.38   539.3  807.65   546.8  806.24   554.3  806.65
   566.7  809.67   606.4  825.61   675.9  858.54   715.6  881.73   814.8   946.7
   854.5  968.61   874.4  978.16     914   988.2   963.7 1014.41   973.6 1019.14
   983.5 1022.05  1003.4 1023.52  1062.9 1024.16  1082.8 1027.39  1092.7 1031.18
#Mann= 3 , 0 , 0
       0      .1       0   539.3    .045       0   554.3      .1       0
Bank Sta=539.3,554.3
XS Rating Curve= 0 ,0
Exp/Cntr=0.3,0.1

Type RM Length L Ch R = 1 ,9646.4  ,201.7,198.1,194.5
XS GIS Cut Line= 3
     1871673.382       420554.72     1872213.351      420473.781
     1872753.455      420393.764
#Sta/Elev= 30
       0  951.19    49.6  941.48   119.1   925.8   148.9  917.79   168.8  910.22
   228.3  882.73   248.2  871.33     268  856.68     278  847.92   297.8  825.06
   307.8  819.37   317.7  819.04   337.5  823.82   347.5  824.91     407  824.12
   466.6  809.75   516.2  808.97   538.5  800.54     546  799.02   553.5  800.21
   585.7  809.19   615.5  815.26   694.9   834.8   714.8  845.62   774.3  887.43
   893.5  954.03  1042.4 1018.32  1052.3 1021.63  1062.2 1023.22    1092 1022.56
#Mann= 3 , 0 , 0
       0      .1       0   538.5    .045       0   553.5      .1       0
Bank Sta=538.5,553.5
XS Rating Curve= 0 ,0
Exp/Cntr=0.3,0.1

Type RM Length L Ch R = 1 ,9448.3  ,395.9,401.8,407.8
XS GIS Cut Line= 2
      1871725.76      420832.166     1872771.194       420502.69
#Sta/Elev= 30
       0 1009.65    89.7  955.84   119.6  936.88   149.5   915.6     269   824.8
     279  819.91     289   818.2   338.8  817.23   418.5  813.39   478.3  804.66
   508.2  802.14   528.1  792.64   531.8  791.91   538.1  790.68   546.8  791.78
   597.9  811.98   657.7  826.71   677.6  833.38   687.6  837.98   707.5  849.49
   757.3  884.62   787.2  900.93     837  934.37     857  944.96   906.8  965.78
   966.6  993.27  1006.4  1008.6  1036.3 1017.37  1056.3 1019.66  1096.1 1020.62
#Mann= 3 , 0 , 0
       0      .1       0   531.8    .045       0   546.8      .1       0
Bank Sta=531.8,546.8
XS Rating Curve= 0 ,0
Exp/Cntr=0.3,0.1

Type RM Length L Ch R = 1 ,9046.4  ,303.3,300,296
XS GIS Cut Line= 3
     1871752.853      421086.554     1872298.278      421061.517
     1872843.715      421036.725
#Sta/Elev= 30
       0 1022.95   208.5  872.64   248.2  845.68   297.8  814.23   307.8  810.17
   317.7  808.58   426.9  804.36   526.2  791.76   538.5  789.32     546  788.46
   553.5  790.05   555.9  790.56   565.8  797.37   585.7  813.05   605.6     824
   625.4  829.96   655.2  836.72   665.1  840.23   744.6  881.85     824  928.08
   893.4  970.39   913.3  984.29     963    1023   982.8 1036.46  1002.6 1046.89
  1012.6 1050.88  1022.5 1054.18  1042.4 1058.61  1052.3 1062.52    1092 1088.81
#Mann= 3 , 0 , 0
       0      .1       0   538.5    .045       0   553.5      .1       0
Bank Sta=538.5,553.5
XS Rating Curve= 0 ,0
Exp/Cntr=0.3,0.1

Type RM Length L Ch R = 1 ,8746.4  ,302.5,300,298.8
XS GIS Cut Line= 3
     1871805.883       421460.92     1872341.991      421357.822
     1872874.692       421236.28
#Sta/Elev= 30
       0 1036.63    99.3     972     139  945.64   347.4  804.07   357.3  798.72
   367.3   796.4   436.7  793.87   506.2  787.14   516.2  785.09   526.1  781.22
     536  778.33   538.4  778.34   545.9  778.36   553.4  780.89   555.9  781.73
   575.7  792.77   585.7  796.59   635.3  808.76   655.2  815.38   665.1  819.77
   675.1   825.4   704.9  846.26   714.8  852.38   814.2  904.98   873.8   941.5
     983 1009.94  1062.5 1065.42  1072.4 1071.13  1082.4 1073.63  1092.3 1074.62
#Mann= 3 , 0 , 0
       0      .1       0   538.4    .045       0   553.4      .1       0
Bank Sta=538.4,553.4
XS Rating Curve= 0 ,0
Exp/Cntr=0.3,0.1

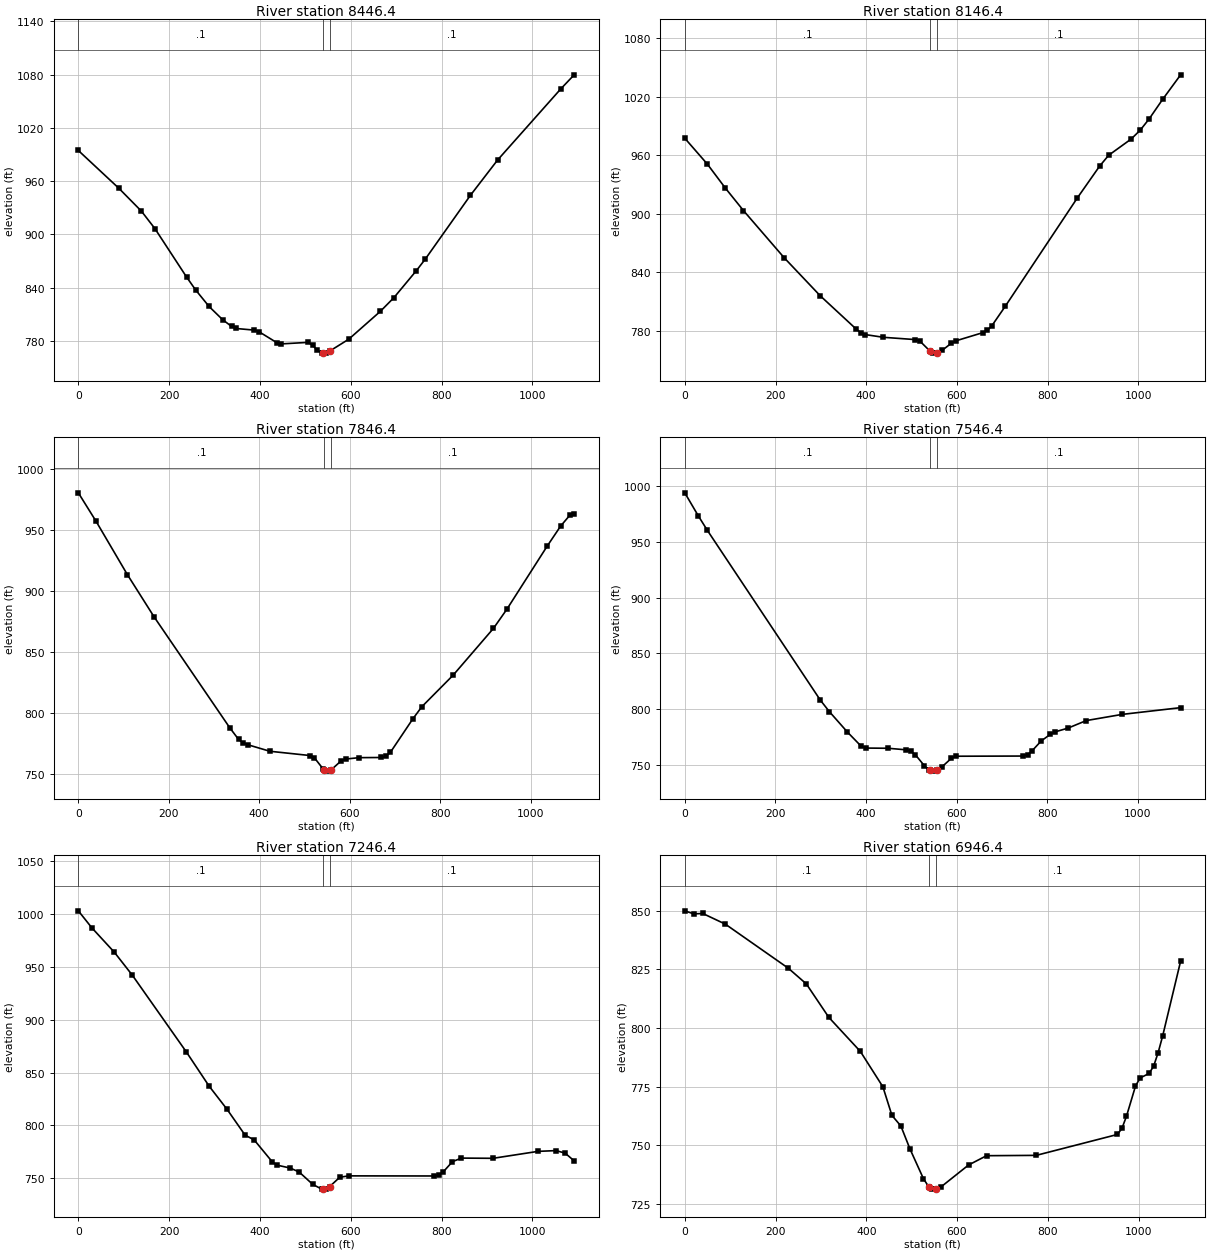
Type RM Length L Ch R = 1 ,8446.4  ,297.1,300,300.5
XS GIS Cut Line= 3
     1871919.926      421802.141     1872441.472      421639.967
     1872966.433      421489.977
#Sta/Elev= 30
       0  994.55    89.4  951.92     139  926.19   168.8  906.48   238.3   852.1
   258.2   837.6     288  818.82   317.8     804   337.6  796.34   347.6  794.04
   387.3  792.22   397.2  790.64   436.9  778.17   446.9  776.68   506.5  778.41
   516.4  775.02   526.3  769.57   536.2  766.29   538.7  766.37   546.2   766.6
   553.7  768.58   595.8  782.02   665.3  813.36   695.1  828.75   744.7  859.25
   764.6  872.44   863.8  944.15   923.4  983.74  1062.4 1063.75  1092.2 1079.79
#Mann= 3 , 0 , 0
       0      .1       0   538.7    .045       0   553.7      .1       0
Bank Sta=538.7,553.7
XS Rating Curve= 0 ,0
Exp/Cntr=0.3,0.1

Type RM Length L Ch R = 1 ,8146.4  ,300.3,300,303.5
XS GIS Cut Line= 3
        1871984.      422022.238     1872523.399      421927.823
     1873051.353      421789.711
#Sta/Elev= 30
       0   977.5    49.8  950.94    89.6  926.31   129.4  903.32     219  855.05
   298.7  815.97   378.3   781.7   388.3  778.08   398.2   776.2   438.1  773.42
   507.8   771.1   517.7  769.87   540.1  759.55   547.6  757.21   555.1  757.33
   567.4  760.04   587.3  767.19   597.2  769.74   656.7  778.14   666.7  780.44
   676.6  784.96   706.4  805.07   865.1  916.01   914.7  948.93   934.6  960.04
   984.2  976.69    1004  985.67  1023.9  997.32  1053.6 1017.34  1093.3 1042.52
#Mann= 3 , 0 , 0
       0      .1       0   540.1    .045       0   555.1      .1       0
Bank Sta=540.1,555.1
XS Rating Curve= 0 ,0
Exp/Cntr=0.3,0.1

Type RM Length L Ch R = 1 ,7846.4  ,296.7,299.9,303.5
XS GIS Cut Line= 3
     1872053.591      422318.853     1872595.305      422215.493
     1873137.632      422161.261
#Sta/Elev= 30
       0  980.49    39.4  957.09   108.3  913.65   167.4  879.07   334.8  788.28
   354.5  778.64   364.4   775.9   374.2  774.41   423.5  769.01   512.1  765.52
   521.9  763.74   541.6  754.42     544  754.02   551.5  752.75     559  753.76
   581.2  761.16   591.1  762.62   620.8  763.77   670.4  763.91   680.3  764.97
   690.2  768.17   739.8  795.54   759.6  805.43     829  831.32   918.1   869.6
   947.9  885.33  1037.1  937.02  1066.8  953.38  1086.6     962  1096.5   963.4
#Mann= 3 , 0 , 0
       0      .1       0     544    .045       0     559      .1       0
Bank Sta=544,559
XS Rating Curve= 0 ,0
Exp/Cntr=0.3,0.1

Type RM Length L Ch R = 1 ,7546.4  ,302.9,300,294.6
XS GIS Cut Line= 3
     1872086.804      422537.611     1872634.669      422511.175
     1873179.185      422545.072
#Sta/Elev= 30
       0  993.96    29.9  973.23    49.9  960.22   299.2  807.96   319.1  797.68
     359  779.33   388.9  766.83   398.9  765.06   448.8  764.87   488.7  763.47
   498.6  762.19   508.6  759.14   528.6  749.23   538.5  745.48     541   745.2
   548.5  744.37     556  745.18   568.3   748.5   588.2  755.87   598.1  757.73
   746.9   757.9   756.8  759.24   766.7  762.77   786.6  771.48   806.4   777.3
   816.3  779.47   846.1  783.02   885.8   789.7   965.1  795.25  1094.1   801.3
#Mann= 3 , 0 , 0
       0      .1       0     541    .045       0     556      .1       0
Bank Sta=541,556
XS Rating Curve= 0 ,0
Exp/Cntr=0.3,0.1

Type RM Length L Ch R = 1 ,7246.4  ,299.7,300,299.8
XS GIS Cut Line= 3
     1872123.456      422905.001     1872660.954      422809.021
     1873198.451       422713.04
#Sta/Elev= 30
       0 1003.25    29.8  987.14    79.4  963.96   119.1  942.16   238.2  869.34
   287.9  837.21   327.6  815.12   367.3  790.67   387.2  786.21   426.9  765.49
   436.8  762.33   466.6  759.52   486.4  755.73   516.2  744.05   536.1  739.53
   538.5  739.57     546  739.69   553.5  741.94   575.8  750.78   595.6  752.09
   784.2  751.99   794.2  752.97   804.1  756.09     824  765.58   843.8  768.94
   913.3  768.73  1012.6  775.32  1052.3  776.03  1072.2  773.62    1092  766.31
#Mann= 3 , 0 , 0
       0      .1       0   538.5    .045       0   553.5      .1       0
Bank Sta=538.5,553.5
XS Rating Curve= 0 ,0
Exp/Cntr=0.3,0.1

Type RM Length L Ch R = 1 ,6946.4  ,354.7,352.4,350.7
XS GIS Cut Line= 3
     1872165.682      423194.771     1872704.167      423105.867
     1873241.936      423005.906
#Sta/Elev= 30
       0  849.99    19.8   848.7    39.7  848.85    89.3  844.32   228.2   825.5
   267.9  818.81   317.5  804.53     387     790   436.6  774.92   456.5  762.74
   476.3  758.19   496.2  748.45   525.9  735.76   538.3  732.07   545.8  731.28
   553.3  731.42   565.7  732.38   625.3  741.56   665.1  745.54   774.5  745.68
   953.5   754.6   963.5  757.21   973.4  762.33   993.3   775.2  1003.2  778.66
  1023.1  780.61  1033.1  783.63    1043  789.34    1053  796.45  1092.8  828.54
#Mann= 3 , 0 , 0
       0      .1       0   538.3    .045       0   553.3      .1       0
Bank Sta=538.3,553.3
XS Rating Curve= 0 ,0
Exp/Cntr=0.3,0.1

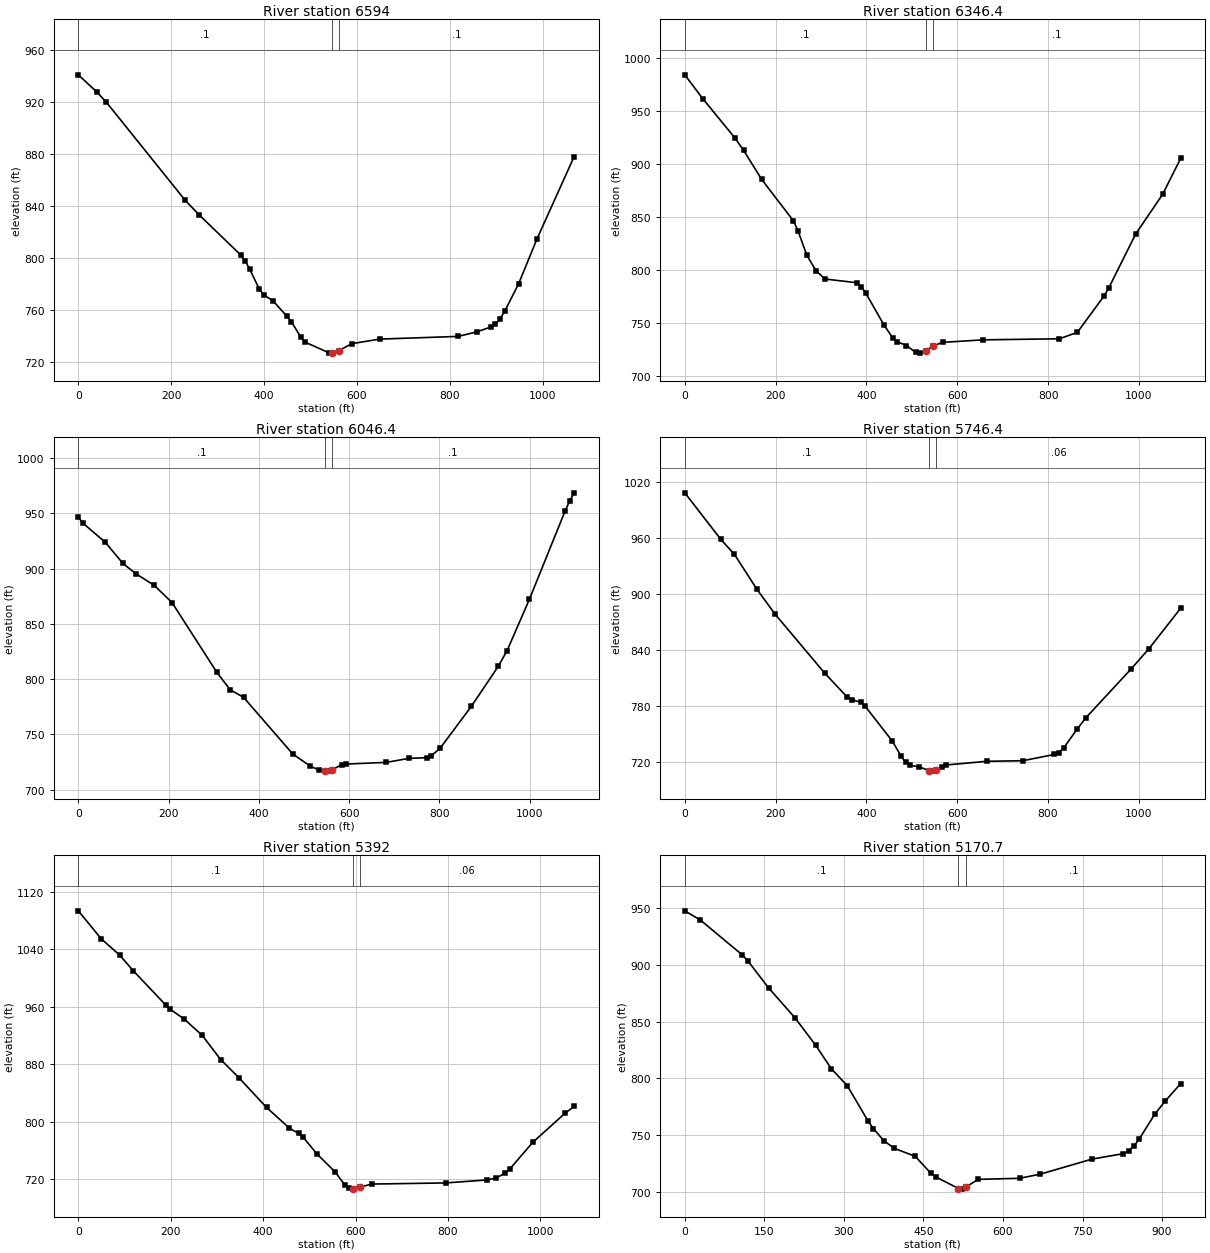
Type RM Length L Ch R = 1 ,6594    ,251.2,247.6,244
XS GIS Cut Line= 2
     1872292.704      423579.199     1873323.809      423300.628
#Sta/Elev= 30
       0  940.63    39.9  927.39    59.9  919.76   229.6  844.38   259.5  833.16
   349.4  802.21   359.4  797.42   369.3  791.08   389.3  776.19   399.3  771.35
   419.2  766.89   449.2  754.92   459.2  750.66   479.1  738.89   489.1  734.95
     539  726.94   545.5   726.7     549  726.57   560.5  728.29   588.9  733.83
   648.8  737.34   818.5  739.44   858.4  742.93   888.4  746.63   898.4  748.78
   908.4  752.94   918.3  758.65   948.3  779.79   988.2  814.58  1068.1  877.77
#Mann= 3 , 0 , 0
       0      .1       0   545.5    .045       0   560.5      .1       0
Bank Sta=545.5,560.5
XS Rating Curve= 0 ,0
Exp/Cntr=0.3,0.1

Type RM Length L Ch R = 1 ,6346.4  ,299.9,300,299.4
XS GIS Cut Line= 3
     1872398.478       423892.77     1872888.731        423671.5
     1873393.694      423444.126
#Sta/Elev= 30
       0  984.12    39.8  961.46   109.6  924.89   129.5  912.79   169.3  885.32
   239.1  846.25     249  837.01   268.9  813.53   288.9   799.1   308.8  791.24
   378.5  787.77   388.5  784.11   398.4  778.06   438.3  747.95   458.2  735.47
   468.2  731.89   488.1  728.43     508  721.97     518  721.25   530.4  723.14
   545.4   727.8   567.5  731.42   656.5  733.78   824.7  734.81   864.2  740.82
   923.6  775.53   933.4  782.72   992.8  833.82  1052.1  871.24  1091.7  905.12
#Mann= 3 , 0 , 0
       0      .1       0   530.4    .045       0   545.4      .1       0
Bank Sta=530.4,545.4
XS Rating Curve= 0 ,0
Exp/Cntr=0.3,0.1

Type RM Length L Ch R = 1 ,6046.4  ,295.2,300,306.1
XS GIS Cut Line= 3
     1872545.953      424147.239     1873052.043      423922.187
       1873543.1      423686.679
#Sta/Elev= 30
       0   946.5     9.9  941.16    59.3  923.92    98.9  904.58   128.6  894.99
   168.1  884.82   207.7  869.14   306.6  806.25   336.3  790.34     366  783.48
   474.8  732.29   514.3  721.04   534.1   717.6   546.4  716.75   553.9  716.67
   561.4  717.71   583.6   722.5   593.5  723.08   682.6  724.59   732.1  728.21
   771.7  728.83   781.6  730.41   801.4   737.3   870.7  775.28   930.2  811.41
     950  825.81   999.5  872.35  1078.7  952.33  1088.6  961.31  1098.5  968.51
#Mann= 3 , 0 , 0
       0      .1       0   546.4    .045       0   561.4      .1       0
Bank Sta=546.4,561.4
XS Rating Curve= 0 ,0
Exp/Cntr=0.3,0.1

Type RM Length L Ch R = 1 ,5746.4  ,357.2,354.3,350.8
XS GIS Cut Line= 3
     1872595.375      424323.883     1873129.937      424211.248
     1873667.297      424114.798
#Sta/Elev= 30
       0 1008.63    79.5  958.62   109.3  942.64   158.9  905.15   198.6  878.65
   307.9  815.38   357.6  789.62   367.5  786.89   387.4  783.92   397.3   779.7
   456.9  742.54   476.8  725.92   486.7  719.41   496.6  716.34   516.5  714.73
   538.8  710.53   546.3  710.14   553.8   711.6   566.2  715.02   576.1  716.74
   665.4  720.68   744.8  721.32   814.3  728.06   824.2   730.1   834.2  734.66
   863.9  755.04   883.8  767.53   983.1  819.68  1022.8  841.64  1092.2  884.79
#Mann= 3 , 0 , 0
       0      .1       0   538.8    .045       0   553.8     .06       0
Bank Sta=538.8,553.8
XS Rating Curve= 0 ,0
Exp/Cntr=0.3,0.1

Type RM Length L Ch R = 1 ,5392    ,234.1,221.3,208.8
XS GIS Cut Line= 2
     1872631.604      424755.728     1873644.912      424402.047
#Sta/Elev= 30
       0 1093.24    49.7 1054.24    89.4 1031.74   119.2 1009.73   188.8  962.55
   198.8  956.35   228.6  943.08   268.3  919.96   308.1  886.45   347.8  861.09
   407.4  819.81   457.1  790.99     477  783.66   486.9  778.28   516.8  755.02
   556.5  729.84   576.4  712.26   586.3   707.2   594.1  706.48   596.2  706.28
   609.1  709.17     636  713.33     795   714.9   884.4  719.03   904.3  721.68
   924.2  728.64   934.1  734.34   983.8  771.38  1053.4   811.7  1073.3  821.25
#Mann= 3 , 0 , 0
       0      .1       0   594.1    .045       0   609.1     .06       0
Bank Sta=594.1,609.1
XS Rating Curve= 0 ,0
Exp/Cntr=0.3,0.1

Type RM Length L Ch R = 1 ,5170.7  ,316.4,324.2,334.9
XS GIS Cut Line= 3
       1873000.4      425143.426      1873338.37      424718.311
      1873603.48      424429.669
#Sta/Elev= 30
       0  947.61    29.6  939.41   108.6  908.68   118.5  903.75     158  879.69
   207.4  853.54   246.9  829.08   276.5  808.32   306.1  793.68   345.6  762.42
   355.5  755.78   375.2  745.06     395   738.3   434.5  731.27   464.1  716.29
     474  712.98     516   702.9   523.3  702.36     531  704.42   552.9  710.94
   631.3   711.9   670.5  715.57   768.4  728.89   827.2  733.64     837  736.05
   846.8  740.33   856.6  746.25     886  768.22   905.6  779.81     935  795.24
#Mann= 3 , 0 , 0
       0      .1       0     516    .045       0     531      .1       0
Bank Sta=516,531
XS Rating Curve= 0 ,0
Exp/Cntr=0.3,0.1

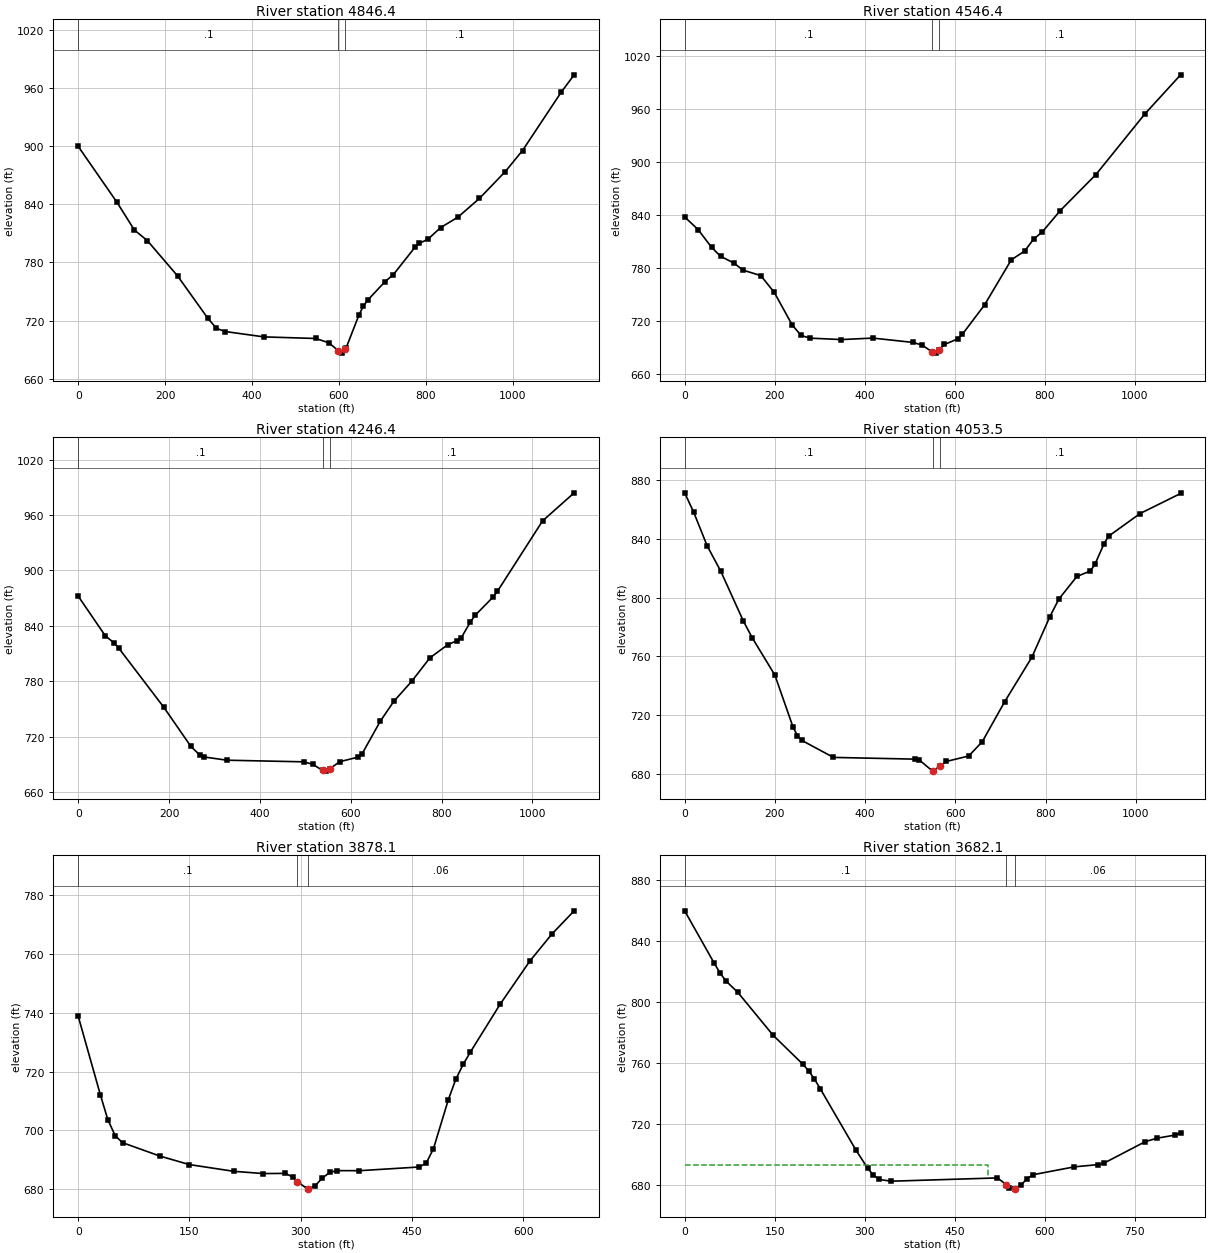
Type RM Length L Ch R = 1 ,4846.4  ,294.3,299.9,301.3
XS GIS Cut Line= 3
      1873067.96      425230.833     1873584.759      424912.838
     1874073.751      424695.424
#Sta/Elev= 30
       0  899.75    89.5  841.87   129.3  813.46   159.2  802.46   228.8  766.02
   298.4  722.34   318.3  711.91   338.2  708.64   427.7  703.09   547.1  701.44
     577  696.98   599.3  688.76   606.8  686.33   614.3  690.25   616.7   691.5
   646.4  725.72   656.4  734.76   666.3  740.91   705.9  759.91   725.7  767.45
   775.3  795.56   785.2  799.69     805  803.84   834.7  816.01   874.4  826.74
   923.9  846.07   983.4  873.82    1023  895.51  1112.2  955.79  1141.9  973.65
#Mann= 3 , 0 , 0
       0      .1       0   599.3    .045       0   614.3      .1       0
Bank Sta=599.3,614.3
XS Rating Curve= 0 ,0
Exp/Cntr=0.3,0.1

Type RM Length L Ch R = 1 ,4546.4  ,293.5,300,307.4
XS GIS Cut Line= 3
     1873116.353      425366.662      1873647.21      425197.692
       1874156.6      425005.972
#Sta/Elev= 30
       0  837.74    29.8  823.44    59.7  803.41    79.6  793.23   109.4  785.55
   129.3   777.6   169.1  771.34     199  752.31   238.8  715.49   258.6  703.58
   278.6  700.57   348.2  698.97   417.8  700.66   507.4  695.71   527.3  692.71
   549.6  684.99   557.1  683.62   564.6  687.04   576.9  693.42   606.6  699.78
   616.5   704.8     666  738.22   725.3  789.19     755  799.17   774.8  812.55
   794.6  821.05   834.2     845   913.4  885.78  1022.2  954.47  1101.4  998.61
#Mann= 3 , 0 , 0
       0      .1       0   549.6    .045       0   564.6      .1       0
Bank Sta=549.6,564.6
XS Rating Curve= 0 ,0
Exp/Cntr=0.3,0.1

Type RM Length L Ch R = 1 ,4246.4  ,188.5,192.9,197.6
XS GIS Cut Line= 3
     1873126.654      425508.069     1873672.491      425495.841
     1874218.263       425475.74
#Sta/Elev= 30
       0   872.2    59.6  829.25    79.4  821.41    89.3  815.89   188.6  751.79
   248.2  709.44     268  700.02     278  698.01   327.6  694.56   496.3  692.81
   516.2  690.17   538.5  683.42     546  682.74   553.5  685.11   575.8  692.92
   615.5  697.83   625.4  701.72   665.1  736.67   694.9  758.26   734.6  780.11
   774.4  805.37   814.1  819.72   833.9  823.89   843.9  827.42   863.7  844.33
   873.7  851.27   913.4  871.12   923.3  877.52  1022.6  953.69  1092.1  984.06
#Mann= 3 , 0 , 0
       0      .1       0   538.5    .045       0   553.5      .1       0
Bank Sta=538.5,553.5
XS Rating Curve= 0 ,0
Exp/Cntr=0.3,0.1

Type RM Length L Ch R = 1 ,4053.5  ,177.6,175.4,173.2
XS GIS Cut Line= 2
     1873124.772      425587.835      1874205.98      425784.864
#Sta/Elev= 30
       0  871.28      20  858.05      50  835.12    79.9  818.02   129.9  784.17
   149.9  772.56   199.8  747.36   239.8  712.26   249.8  706.03   259.8  702.86
   329.7  691.34   509.5  690.17   519.5  689.69   549.5  682.01   549.7  682.04
   564.7  685.19   579.5  688.57   629.4   692.3   659.4     702   709.4  729.35
   769.3  759.43   809.3  787.09   829.3  799.08   869.2  814.41   899.2  818.16
   909.2   822.7   929.2  836.61   939.2  841.74  1009.1  857.18    1099  870.84
#Mann= 3 , 0 , 0
       0      .1       0   549.7    .045       0   564.7      .1       0
Bank Sta=549.7,564.7
XS Rating Curve= 0 ,0
Exp/Cntr=0.3,0.1

Type RM Length L Ch R = 1 ,3878.1  ,202.2,196,189.7
XS GIS Cut Line= 2
     1873314.429      425831.508     1873981.828      425874.721
#Sta/Elev= 30
       0  738.84      30  711.97    39.9  703.65    49.9  698.13    59.9  695.77
   109.8  691.25   149.7  688.33   209.6  686.03   249.6  685.26   279.5  685.32
   289.5  684.05   295.5  682.54   309.4  679.96   310.5  680.09   319.4   681.1
   329.4  683.77   339.4  685.68   349.4  686.26   379.3  686.24   459.2  687.49
   469.2  688.76   479.1  693.75   499.1  710.41   509.1  717.31   519.1  722.43
     529   726.7     569  742.94   608.9  757.58   638.8  766.83   668.8  774.74
#Mann= 3 , 0 , 0
       0      .1       0   295.5    .045       0   310.5     .06       0
Bank Sta=295.5,310.5
XS Rating Curve= 0 ,0
Exp/Cntr=0.3,0.1

Type RM Length L Ch R = 1 ,3682.1  ,185.2,195,204.8
XS GIS Cut Line= 3
     1873104.366      426055.975     1873396.484      426096.355
     1873915.809      425982.753
#Sta/Elev= 30
       0   859.8    49.2  825.48      59  818.99    68.8  813.81    88.5  806.37
   147.4  778.22   196.6  759.38   206.4  755.05   216.3   749.5   226.1  743.08
   285.1  703.17   304.7  691.22   314.6  686.45   324.4   683.7   344.1  682.57
   521.3  684.73   535.9  680.37     541  678.42   550.8  677.38   550.9  677.41
   560.7  680.12   570.5  684.23   580.4  686.81   649.3  691.98   688.7  693.43
   698.5  694.36   767.4  708.47   787.1  710.76   816.7  712.77   826.5  714.14
#Mann= 3 , 0 , 0
       0      .1       0   535.9    .045       0   550.9     .06       0
#XS Ineff= 2 , 0
          504.78  693.06
Permanent Ineff=
       F       F
Bank Sta=535.9,550.9
XS Rating Curve= 0 ,0
Exp/Cntr=0.3,0.1

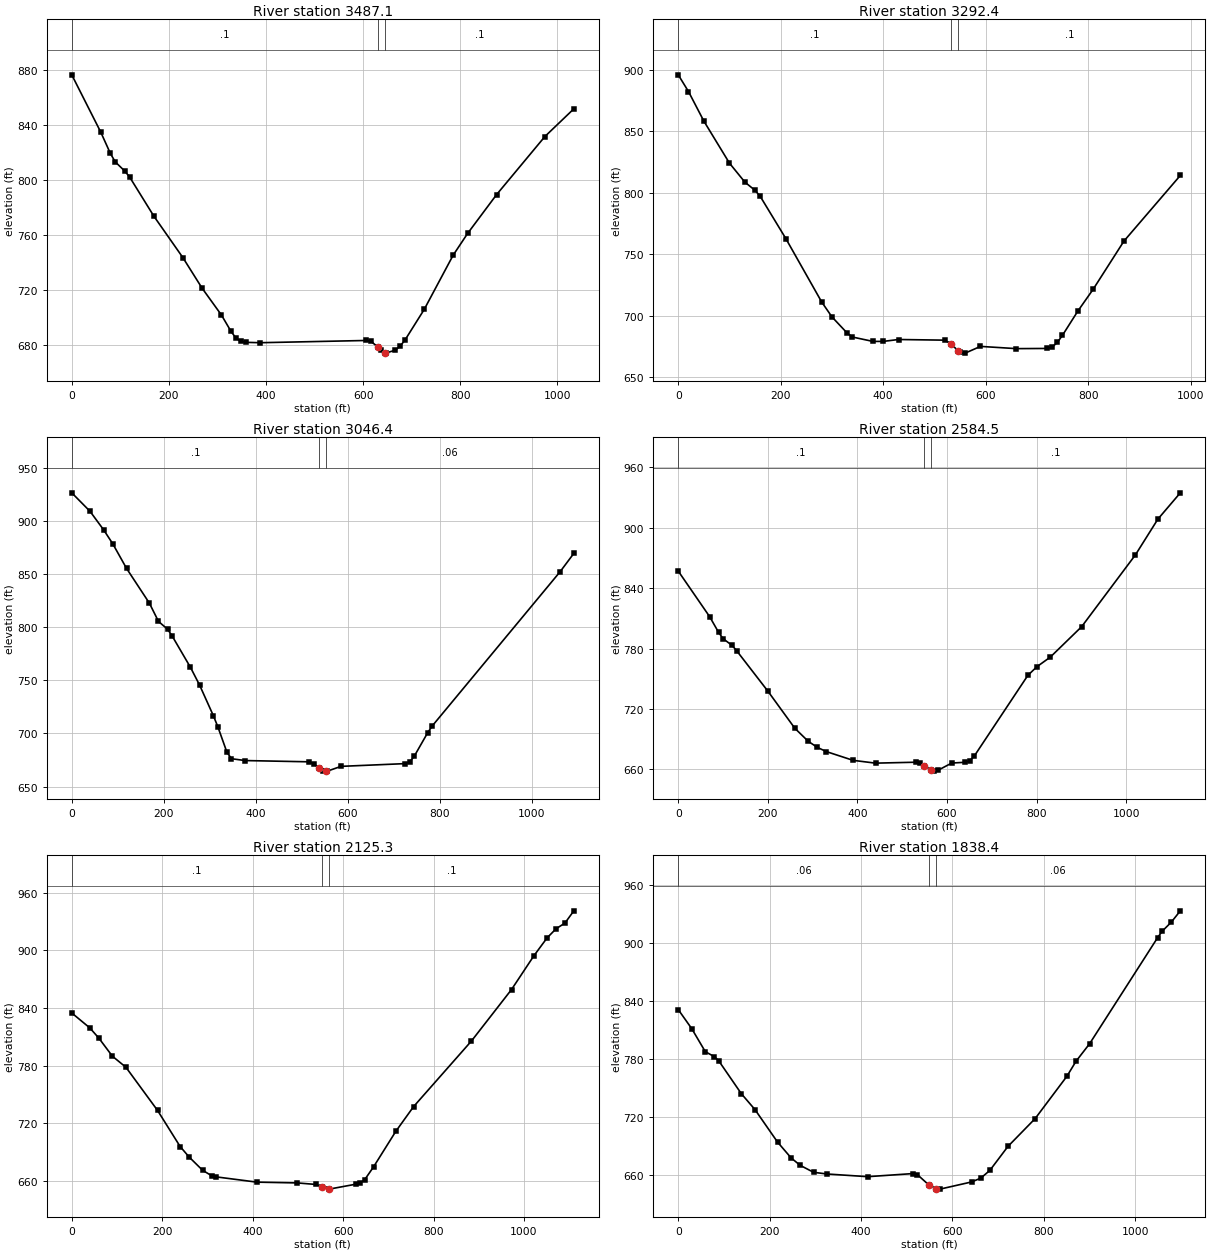
Type RM Length L Ch R = 1 ,3487.1  ,190.3,194.6,199
XS GIS Cut Line= 2
     1873086.787      426079.677     1874097.219       426299.32
#Sta/Elev= 30
       0  876.55    59.7  834.89    79.5   819.4    89.5  813.28   109.4   806.5
   119.3  802.18     169  773.84   228.7  743.75   268.4  721.46   308.2  701.96
   328.1  689.98     338  685.25     348   682.8   357.9   682.1   387.8  681.82
   606.5  683.45   616.4  682.78     631  678.47   636.3  676.32     646  674.31
   646.3  674.25   666.2  676.38   676.1  679.31     686  683.61   725.8     706
   785.5  745.48   815.3  761.29     875  789.53   974.4  831.71    1034  851.84
#Mann= 3 , 0 , 0
       0      .1       0     631    .045       0     646      .1       0
Bank Sta=631,646
XS Rating Curve= 0 ,0
Exp/Cntr=0.3,0.1

Type RM Length L Ch R = 1 ,3292.4  ,247.7,245.9,244
XS GIS Cut Line= 2
     1873074.202      426137.263       1873978.1      426515.115
#Sta/Elev= 30
       0  895.85      20  882.27      50  858.25     100  824.06     130  808.69
     150  801.93     160  797.07   209.9  762.84   279.9  711.29   299.9  699.19
   329.9  685.91   339.9  682.81   379.9  679.25   399.9  679.25   429.9   680.8
   519.8  680.27   531.8  677.38   546.8  671.36   549.8  670.32   559.8  669.73
   589.8   675.2   659.8  673.38   719.8  673.53   729.8  674.69   739.8  678.44
   749.8  684.24   779.8  703.92   809.8  721.71   869.7  760.75   979.7  814.08
#Mann= 3 , 0 , 0
       0      .1       0   531.8    .045       0   546.8      .1       0
Bank Sta=531.8,546.8
XS Rating Curve= 0 ,0
Exp/Cntr=0.3,0.1

Type RM Length L Ch R = 1 ,3046.4  ,461.2,461.9,462.6
XS GIS Cut Line= 3
      1872988.42      426413.259     1873508.397      426579.813
     1874028.373      426746.368
#Sta/Elev= 30
       0  926.56    39.7  909.16    69.5  891.59    89.4  878.41   119.1  855.42
   168.8  822.68   188.6  805.48   208.5  798.08   218.4  791.71   258.1  762.27
     278  745.56   307.8  716.87   317.7   706.3   337.5  682.25   347.4  676.22
   377.2  674.48   516.2   673.3   526.2  671.53   538.5  667.14     546  665.12
   553.5  664.67   555.9  664.53   585.7  669.02   724.7  671.59   734.6  673.03
   744.6  678.35   774.3  700.84   784.2  707.18  1062.2  852.32    1092  869.57
#Mann= 3 , 0 , 0
       0      .1       0   538.5    .045       0   553.5     .06       0
Bank Sta=538.5,553.5
XS Rating Curve= 0 ,0
Exp/Cntr=0.3,0.1

Type RM Length L Ch R = 1 ,2584.5  ,450,458.8,466.9
XS GIS Cut Line= 2
     1872814.532      426820.682     1873872.792      427190.123
#Sta/Elev= 30
       0     857    70.1  811.69    90.1  796.08   100.1  789.79   120.1  783.14
   130.1  777.99   200.2  737.58   260.2  700.76   290.2  687.77   310.2   681.8
   330.3  677.58   390.3  668.83   440.4  666.04   530.4  666.96   540.4  666.04
   549.1  663.45   564.1  659.01   570.4   658.1   580.5  659.06   610.5  666.13
   640.5  666.89   650.5   668.4   660.5   672.8   780.6  753.34   800.6  761.86
   830.7  771.48   900.7  801.76  1020.8   873.2  1070.8  908.64  1120.9  934.81
#Mann= 3 , 0 , 0
       0      .1       0   549.1    .045       0   564.1      .1       0
Bank Sta=549.1,564.1
XS Rating Curve= 0 ,0
Exp/Cntr=0.3,0.1

Type RM Length L Ch R = 1 ,2125.3  ,289.6,286.7,283.7
XS GIS Cut Line= 3
     1872737.086      427005.569     1873143.837      427389.012
     1873558.154      427752.509
#Sta/Elev= 30
       0  834.93    39.9  819.39    59.9  808.74    89.8  789.96   119.8  778.41
   189.7   733.5   239.6  695.97   259.5  685.02   289.5  671.15   309.4  665.56
   319.4  664.36   409.3  658.89   499.1  658.07     539  656.52     554   654.3
   568.8  651.62     569  651.62   627.9  656.72   637.7  657.94   647.6  661.37
   667.3  674.77   716.5  711.73   755.8  737.46   883.8  805.77   972.4  859.34
  1021.6  894.28  1051.1   913.1  1070.8  922.52  1090.5  928.48  1110.2  941.22
#Mann= 3 , 0 , 0
       0      .1       0     554    .045       0     569      .1       0
Bank Sta=554,569
XS Rating Curve= 0 ,0
Exp/Cntr=0.3,0.1

Type RM Length L Ch R = 1 ,1838.4  ,305.3,297.6,290.3
XS GIS Cut Line= 3
     1872552.297      427298.937     1873000.264      427622.744
     1873452.895      427927.735
#Sta/Elev= 30
       0  831.21    29.6  811.48    59.2  787.79      79   782.6    88.8   778.2
   138.2   744.3   167.8  728.06   217.2  694.52   246.8  678.23   266.5  670.55
   296.1  663.28   325.7  661.53   414.6  658.77   513.3  661.96   523.1  660.93
   548.4   650.2   563.4  646.29   572.6  645.92   642.1  653.36   661.9  657.26
   681.8  665.24   721.4     690     781  718.77   850.4   762.4   870.3  777.86
   900.1     796  1048.9  905.46  1058.8  912.06  1078.7  921.38  1098.5  933.11
#Mann= 3 , 0 , 0
       0     .06       0   548.4    .045       0   563.4     .06       0
Bank Sta=548.4,563.4
XS Rating Curve= 0 ,0
Exp/Cntr=0.3,0.1

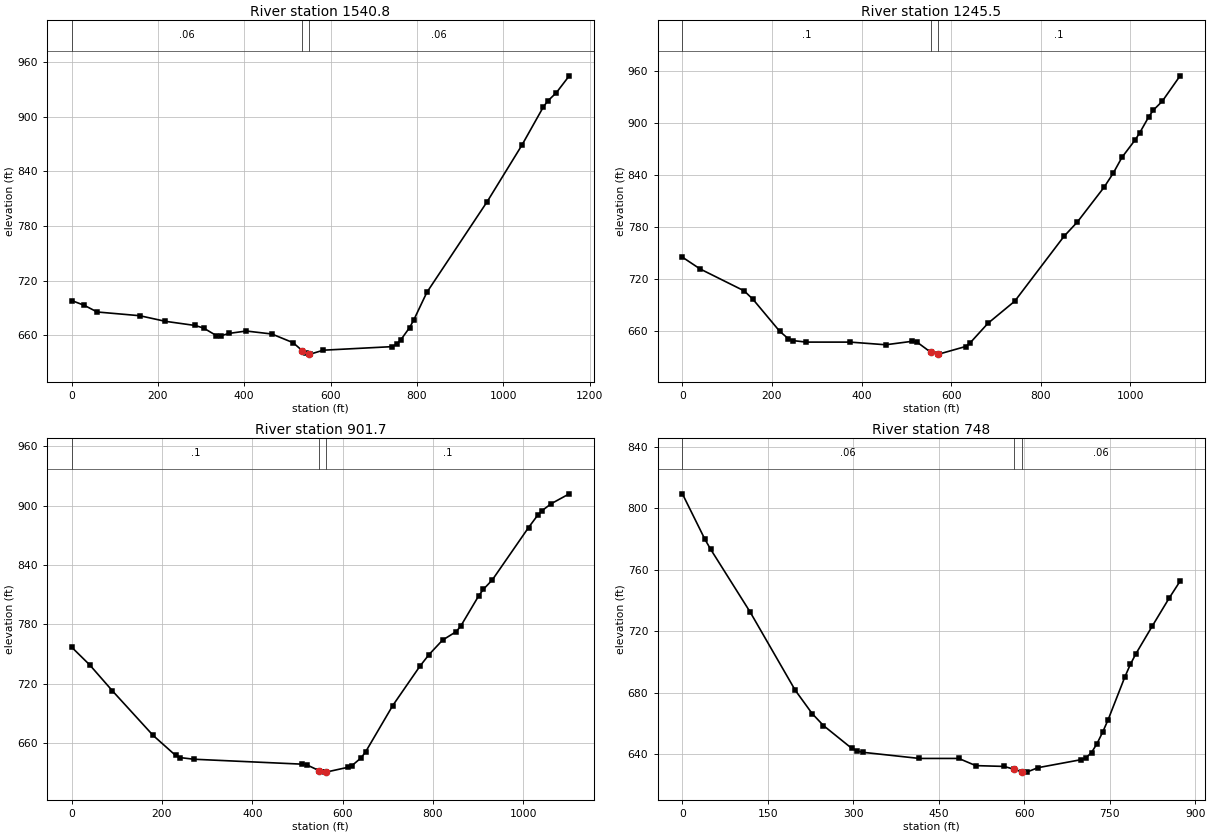
Type RM Length L Ch R = 1 ,1540.8  ,304,295.2,287.4
XS GIS Cut Line= 3
     1872294.261      427703.703     1872807.483      427847.409
     1873408.567      427998.903
#Sta/Elev= 30
       0  698.33    29.6  693.02    59.2  685.74   157.9  681.64   217.1  675.49
   286.2  670.92     306  668.07   335.6  659.74   345.4  659.56   365.2  662.24
   404.7  664.83   463.9  661.56   513.2  652.01     534   643.4     543   640.4
     549  639.84     553  639.46     583  643.77   742.9  647.69   752.9  650.33
   762.9  655.35   782.9  668.52   792.9  677.18   822.9  707.22   962.9  807.01
  1042.9   868.7  1092.8  910.84  1102.8  917.26  1122.8  926.42  1152.8     945
#Mann= 3 , 0 , 0
       0     .06       0     534    .045       0     549     .06       0
Bank Sta=534,549
XS Rating Curve= 0 ,0
Exp/Cntr=0.3,0.1

Type RM Length L Ch R = 1 ,1245.5  ,333.8,343.8,353.3
XS GIS Cut Line= 3
     1872306.528      428201.588     1872864.862      428133.876
     1873411.089      428081.852
#Sta/Elev= 30
       0  745.12    39.5  731.55   138.1  706.22   157.9  696.33   217.1  659.74
   236.8  650.96   246.7  648.95   276.3  647.21     375  647.19   453.9  644.13
   513.1  648.14     523  647.47   554.9  635.33   569.9  633.36   572.4  633.34
   632.3  642.12   642.2  646.23   682.1  668.85     742  694.41   851.7  769.02
   881.7  785.65   941.5  825.81   961.5  841.69   981.4  860.26  1011.4  880.78
  1021.3  888.83  1041.3  907.08  1051.3  914.62  1071.2  924.83  1111.1   954.2
#Mann= 3 , 0 , 0
       0      .1       0   554.9    .045       0   569.9      .1       0
Bank Sta=554.9,569.9
XS Rating Curve= 0 ,0
Exp/Cntr=0.3,0.1

Type RM Length L Ch R = 1 ,901.7   ,160.2,153.6,146.9
XS GIS Cut Line= 2
     1872299.755       428288.23     1873343.677      428640.052
#Sta/Elev= 30
       0  757.11    40.1  739.16    90.1  713.07   180.3  667.99   230.3  647.67
   240.4   645.5   270.4  643.84   510.8  638.84   520.8  638.12   548.7  632.17
   560.8  630.81   563.7  630.86   610.9  635.61   620.9  637.49   640.9  645.22
     651   651.4     711   698.1   771.1  737.82   791.2  749.52   821.2  764.15
   851.2  772.65   861.3   778.2   901.3  808.94   911.3  815.32   931.4  825.01
  1011.5  877.84  1031.5  890.12  1041.5  894.93  1061.6  901.89  1101.6  911.88
#Mann= 3 , 0 , 0
       0      .1       0   548.7    .045       0   563.7      .1       0
Bank Sta=548.7,563.7
XS Rating Curve= 0 ,0
Exp/Cntr=0.3,0.1

Type RM Length L Ch R = 1 ,748     ,744.5,748.1,751.6
XS GIS Cut Line= 5
     1872185.702      428571.989     1872679.633      428603.919
     1872799.051      428608.338     1872892.718      428615.685
     1873057.095      428632.214
#Sta/Elev= 30
       0  809.31    39.6  779.68    49.5  773.31   118.8  732.53     198  681.64
   227.7  666.46   247.5  658.68     297  643.91   306.9  642.13   316.8  641.26
   415.8  637.27   485.1  637.27   514.9   632.6   564.7  632.08   581.7  630.28
   596.7  628.42   604.5  628.37   623.9  631.24     699  636.41   708.4  637.74
   718.1   641.1   727.8  646.93   737.6  654.31   747.3  662.48   776.4  690.04
   786.2  698.36   795.9  705.25     825  723.47   854.2  741.39   873.6  752.52
#Mann= 3 , 0 , 0
       0     .06       0   581.7    .045       0   596.7     .06       0
Bank Sta=581.7,596.7
XS Rating Curve= 0 ,0
Exp/Cntr=0.3,0.1

Chan Stop Cuts=-1
Use User Specified Reach Order=0
Composite Channel Slope=5